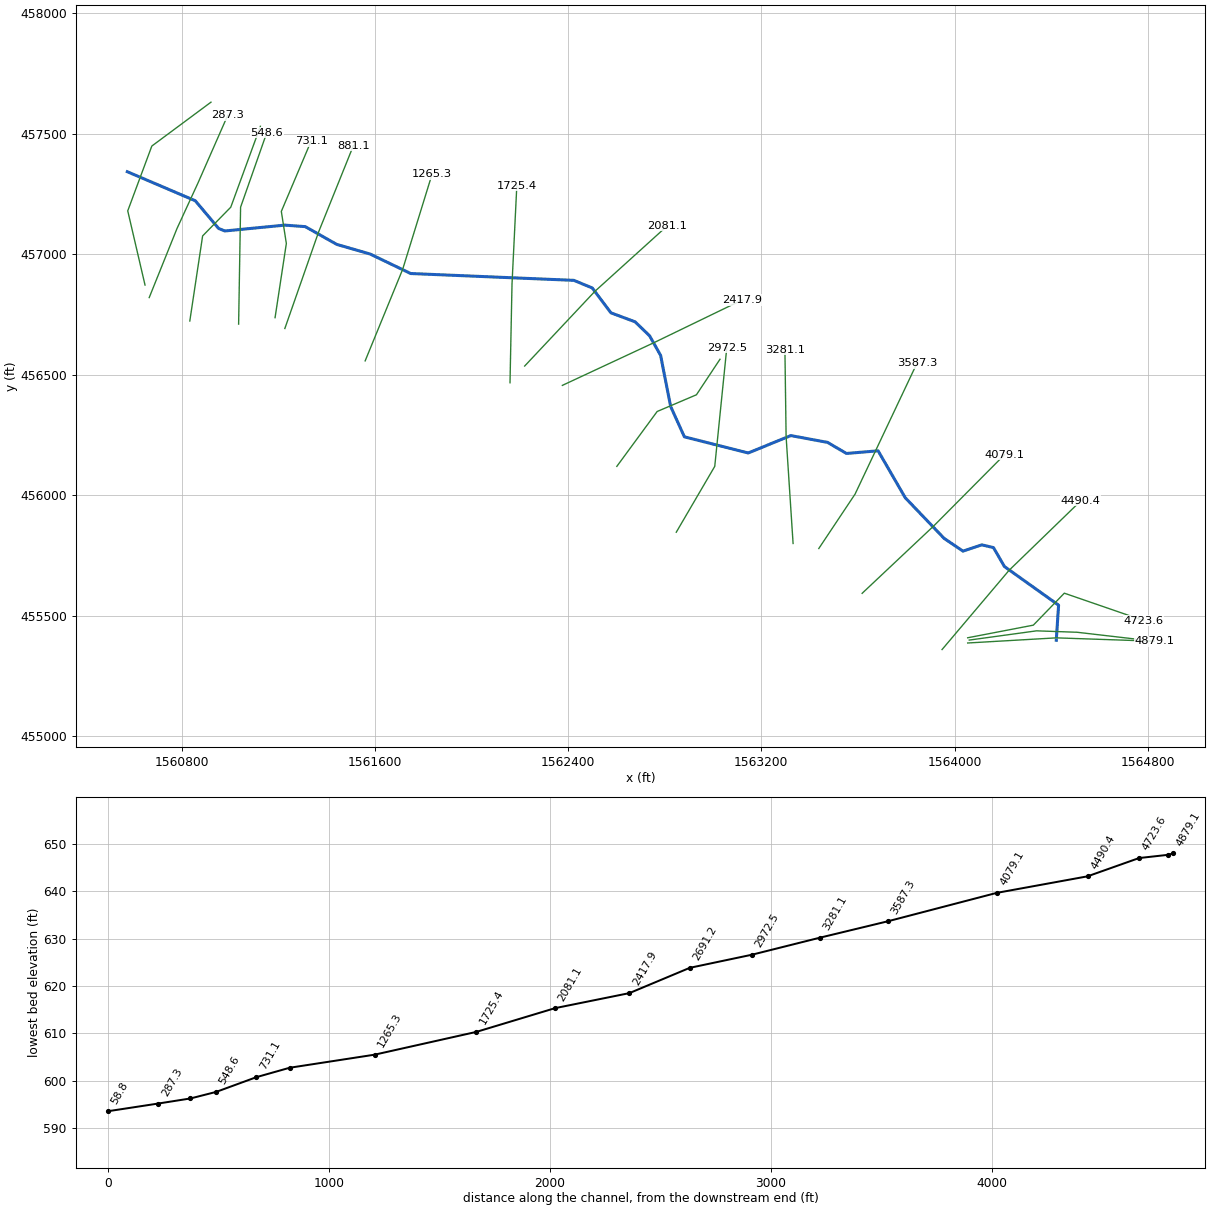
--- MFWILSONCR.prj (project) ---

Proj Title=MFWILSONCR
Current Plan=p01
Default Exp/Contr=0,0
English Units
Geom File=g01
Flow File=f01
Plan File=p01
BEGIN DESCRIPTION:
END DESCRIPTION:
DSS Export Rating Curves= 0
DSS Export Rating Curve Sorted= 0
DSS Export Volume Flow Curves= 0
DXF OffsetX= 0
DXF OffsetY= 0
DXF ScaleX= 0
DXF ScaleY= 0

--- MFWILSONCR.p01 (plan) ---

Plan Title=Floodplain
Program Version=4.00
Geom File=g01
Flow File=f01
K Sum by GR=0
Std Step Tol=0.01
Critical Tol=0.01
Num of Std Step Trials=20
Max Error Tol=0.3
Flow Tol Ratio=0.001
Split Flow NTrial=30
Split Flow Tol=0.02
Split Flow Ratio=0.02
Log Output Level=0
Friction Slope Method=1
Unsteady Friction Slope Method=2
Unsteady Bridges Friction Slope Method=1
Global Log Level=0
CheckData=False
Run HTab=0
Run UNet=0
Run PostProcess=0
UNET Theta=0
UNET Theta Warmup=0
UNET ZTol=0
UNET ZSATol=0
UNET MxIter=0
UNET MaxInSteps=0
UNET DtIC=0
UNET DtMin=0
UNET MaxCRTS=0
UNET WFStab=0
UNET SFStab=0
UNET WFX=0
UNET SFX=0
UNET DSS MLevel=0
UNET DZMax Abort=0
UNET Convert EG Bridges=0
UNET Use Existing IB Tables=0
UNET Froude Limit=0
UNET Froude Power=0
Write IC File=0
Echo Input=False
Echo Output=False
Write Detailed=0

--- MFWILSONCR.f01 (steady flow) ---

Flow Title=NFF Regression Equation
Program Version=4.00
Number of Profiles= 1
Profile Names=P100yr
River Rch & RM=MFWILSONCR,Main            ,4879.1
     331
River Rch & RM=MFWILSONCR,Main            ,4490.4
     432
River Rch & RM=MFWILSONCR,Main            ,3587.3
     462
River Rch & RM=MFWILSONCR,Main            ,2691.2
     493
River Rch & RM=MFWILSONCR,Main            ,287.3
     531
Boundary for River Rch & Prof#=MFWILSONCR,Main            , 1
Up Type= 0
Dn Type= 3
Dn Slope=0.019
DSS Import GetInterval= 0
DSS Import GetPeak= 0
DSS Import FillOption= 0

--- MFWILSONCR.g01 (geometry) ---

Geom Title=USGS 10m DEM
Program Version=4.00

River Reach=MFWILSONCR      ,Main
Reach XY= 30
     1564421.153      455398.672     1564430.731      455544.319
     1564206.478       455704.63     1564161.158      455783.099
     1564112.796      455794.457     1564034.977      455768.471
     1563956.911      455821.247     1563796.008      455989.816
     1563683.606      456184.573      1563552.62      456173.623
     1563474.306      456219.505     1563322.202      456247.767
     1563146.083      456175.599     1562881.709      456242.572
     1562824.793      456368.597     1562783.244      456580.411
     1562737.588      456661.757      1562677.66      456719.633
     1562577.554      456757.058     1562500.214      456860.195
     1562424.092        456891.7     1561748.778      456920.023
     1561580.537      457000.986     1561442.723      457040.825
     1561312.409      457114.494      1561227.67      457120.796
     1560979.343      457096.575     1560953.455      457107.045
     1560857.091      457221.895     1560575.398      457342.418

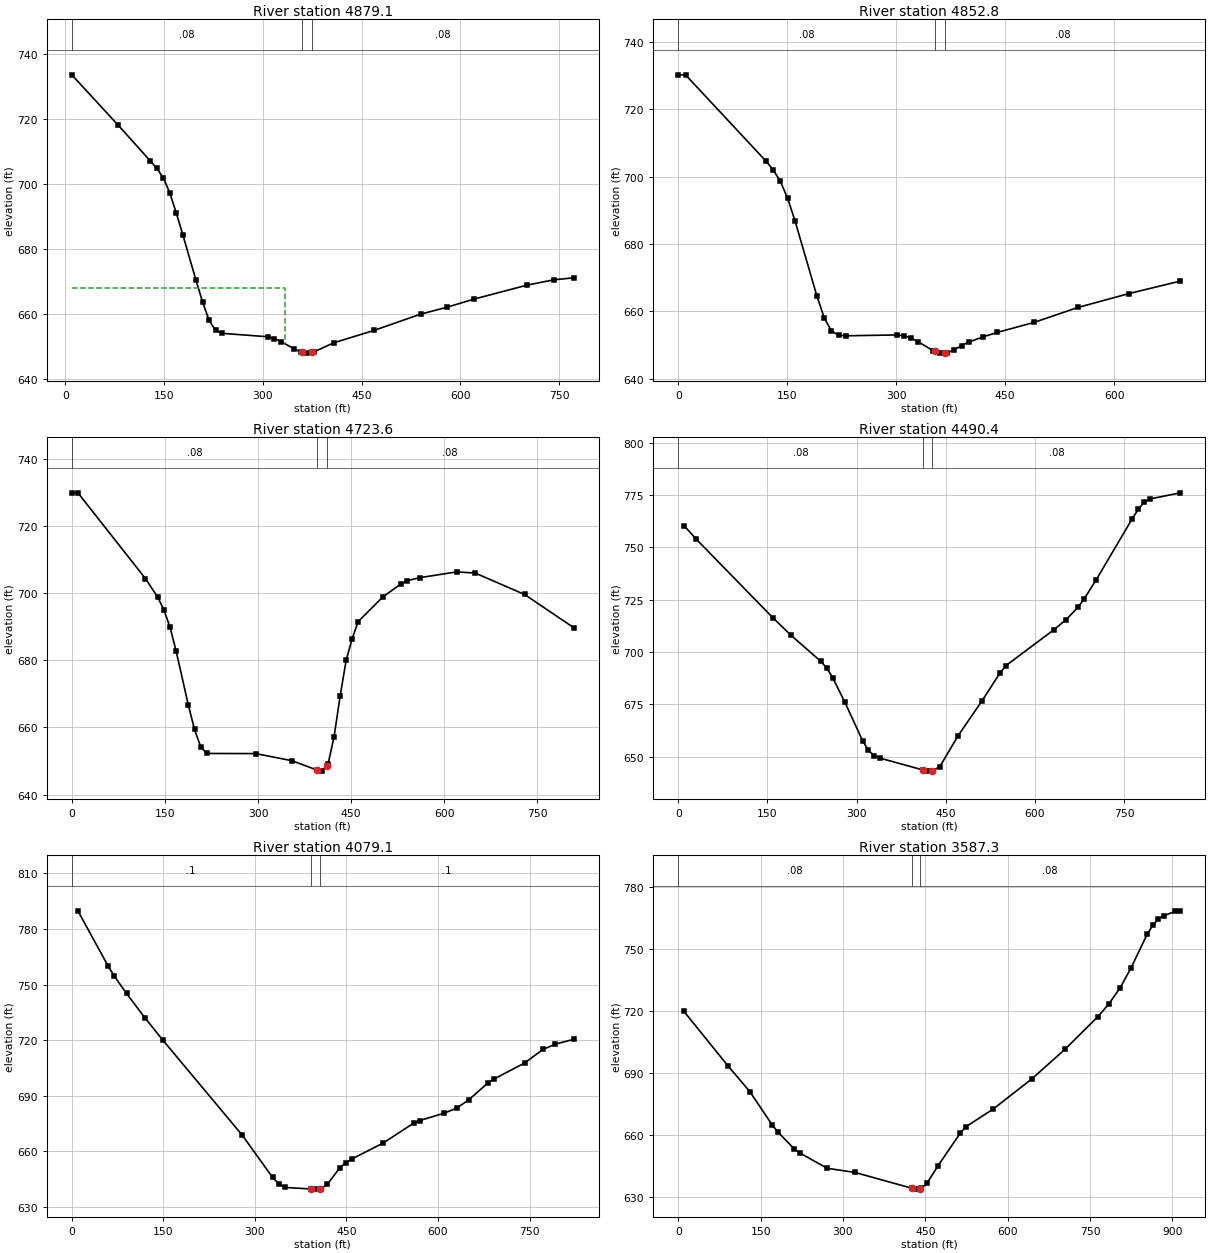
Type RM Length L Ch R = 1 ,4879.1  ,28.3,26.3,26.2
XS GIS Cut Line= 3
     1564054.371      455387.355     1564421.215      455408.672
     1564825.993      455394.827
#Sta/Elev= 30
     9.9   733.5    79.5  718.23   129.1  707.06     139  704.78     149  701.83
   158.9  697.14   168.8  690.92   178.8  684.18   198.6  670.37   208.6  663.65
   218.5  658.05   228.4  654.96   238.4  654.05   307.9     653   317.8  652.44
   327.7  651.53   347.6   649.3   357.5  648.34     360  648.25   367.5  647.97
     375  648.25   377.6  648.34     408  651.16   468.7  654.93   539.6  659.94
   580.1  662.09   620.6  664.56   701.6  668.88   742.1  670.51   772.5  671.11
#Mann= 3 , 0 , 0
     9.9     .08       0     360    .045       0     375     .08       0
#XS Ineff= 2 , 0
          333.96  667.94
Permanent Ineff=
       F       F
Bank Sta=360,375
XS Rating Curve= 0 ,0
Exp/Cntr=0.3,0.1

Type RM Length L Ch R = 1 ,4852.8  ,109.8,129.2,148.6
XS GIS Cut Line= 4
     1564060.896      455399.454     1564339.464      455437.776
     1564507.489       455431.88     1564747.735      455403.876
#Sta/Elev= 30
       0  730.15      10  730.15   120.5  704.65   130.6  702.03   140.6  698.57
   150.6  693.57   160.7  686.92   190.8  664.66   200.9  658.18   210.9  654.23
   220.9  652.95     231   652.8     301  653.05   310.9  652.81   320.8  652.09
   330.6     651   350.4  648.42   352.8  648.24   360.3  647.66   367.8  647.72
   370.2  647.73   380.1  648.62     390  649.91   399.9  650.93   419.6  652.47
   439.4  653.81   489.6  656.75   550.1  661.19   620.6  665.32   691.2  669.01
#Mann= 3 , 0 , 0
       0     .08       0   352.8    .045       0   367.8     .08       0
Bank Sta=352.8,367.8
XS Rating Curve= 0 ,0
Exp/Cntr=0.3,0.1

Type RM Length L Ch R = 1 ,4723.6  ,231.8,233.2,232.5
XS GIS Cut Line= 4
     1564054.371      455409.032     1564326.199      455461.358
     1564454.428      455594.009     1564782.715      455480.566
#Sta/Elev= 30
       0  729.84     9.9  729.84   118.6  704.33   138.4  698.78   148.3  695.03
   158.2  689.87   168.1  682.73   187.8  666.62   197.7  659.39   207.6  654.26
   217.5  652.25   296.2  652.21   354.5   650.1   395.6  647.27   403.1  646.99
   410.6   648.6   412.8  649.08   422.5  657.23   432.2  669.26   441.9  679.94
   451.6  686.39   461.3   691.5     501  698.84   530.8  702.79   540.7  703.71
   560.6  704.58   620.1  706.31   649.9  705.95   729.3  699.58   808.7  689.68
#Mann= 3 , 0 , 0
       0     .08       0   395.6    .045       0   410.6     .08       0
Bank Sta=395.6,410.6
XS Rating Curve= 0 ,0
Exp/Cntr=0.3,0.1

Type RM Length L Ch R = 1 ,4490.4  ,413.6,411.3,411.8
XS GIS Cut Line= 3
     1563948.302      455360.142     1564225.618      455688.664
     1564522.878      455977.317
#Sta/Elev= 30
      10  760.33      30  754.03     160  716.14     190  707.95     240  695.51
     250   692.3     260  687.62   279.9  676.23   309.9  657.75   319.9  653.01
   329.9  650.34   339.9  649.29   412.4  643.62   419.9  643.13   427.4  643.19
     440  645.32   470.3   659.9   510.8  676.69   541.1  690.03   551.2  693.57
     632  710.73   652.3  715.54   672.5  721.48   682.6  725.41   702.8   734.5
   763.4  763.68   773.5  768.15   783.6  771.64   793.7  773.18   844.3  776.08
#Mann= 3 , 0 , 0
       0     .08       0   412.4    .045       0   427.4     .08       0
Bank Sta=412.4,427.4
XS Rating Curve= 0 ,0
Exp/Cntr=0.3,0.1

Type RM Length L Ch R = 1 ,4079.1  ,473.3,491.8,509.6
XS GIS Cut Line= 3
     1563617.537      455593.421     1563914.785      455873.841
     1564206.109      456167.724
#Sta/Elev= 30
      10  789.78    59.8  759.85    69.8  754.52    89.7   745.2   119.6  732.15
   149.5  719.89   279.1  668.81   328.9  645.97   338.9   642.6   348.8  640.55
   391.2  639.71   398.7  639.63   406.2  639.88   408.6  639.96   418.7  642.23
   438.9  651.05     449  653.95   459.1  655.95   509.6  664.41     560   675.2
   570.1  676.64   610.5  680.66   630.7  683.35   650.9  687.97   681.2  696.75
   691.2  698.94   741.7  707.65     772     715   792.2  717.85   822.5  720.46
#Mann= 3 , 0 , 0
       0      .1       0   391.2    .045       0   406.2      .1       0
Bank Sta=391.2,406.2
XS Rating Curve= 0 ,0
Exp/Cntr=0.3,0.1

Type RM Length L Ch R = 1 ,3587.3  ,306.1,306.2,305.6
XS GIS Cut Line= 3
     1563438.105      455779.259     1563588.317      456005.147
     1563844.866       456548.78
#Sta/Elev= 30
      10  719.93    90.4  693.45   130.6  680.84   170.8  664.91   180.8  661.53
     211  653.22     221  651.22   271.3  643.75   321.7  641.73   425.2   634.1
   432.7  633.64   440.2  633.89   442.8  633.98   452.9  636.44     473  644.93
   513.4   660.7   523.5  663.82   573.6  672.47   643.8  687.04   703.9  701.34
     764  717.17   784.1   723.4   804.1  730.98   824.1  740.62   854.2  757.33
   864.2  761.52   874.2  764.62   884.3  766.16   904.3  768.23   914.3  768.55
#Mann= 3 , 0 , 0
       0     .08       0   425.2    .045       0   440.2     .08       0
Bank Sta=425.2,440.2
XS Rating Curve= 0 ,0
Exp/Cntr=0.3,0.1

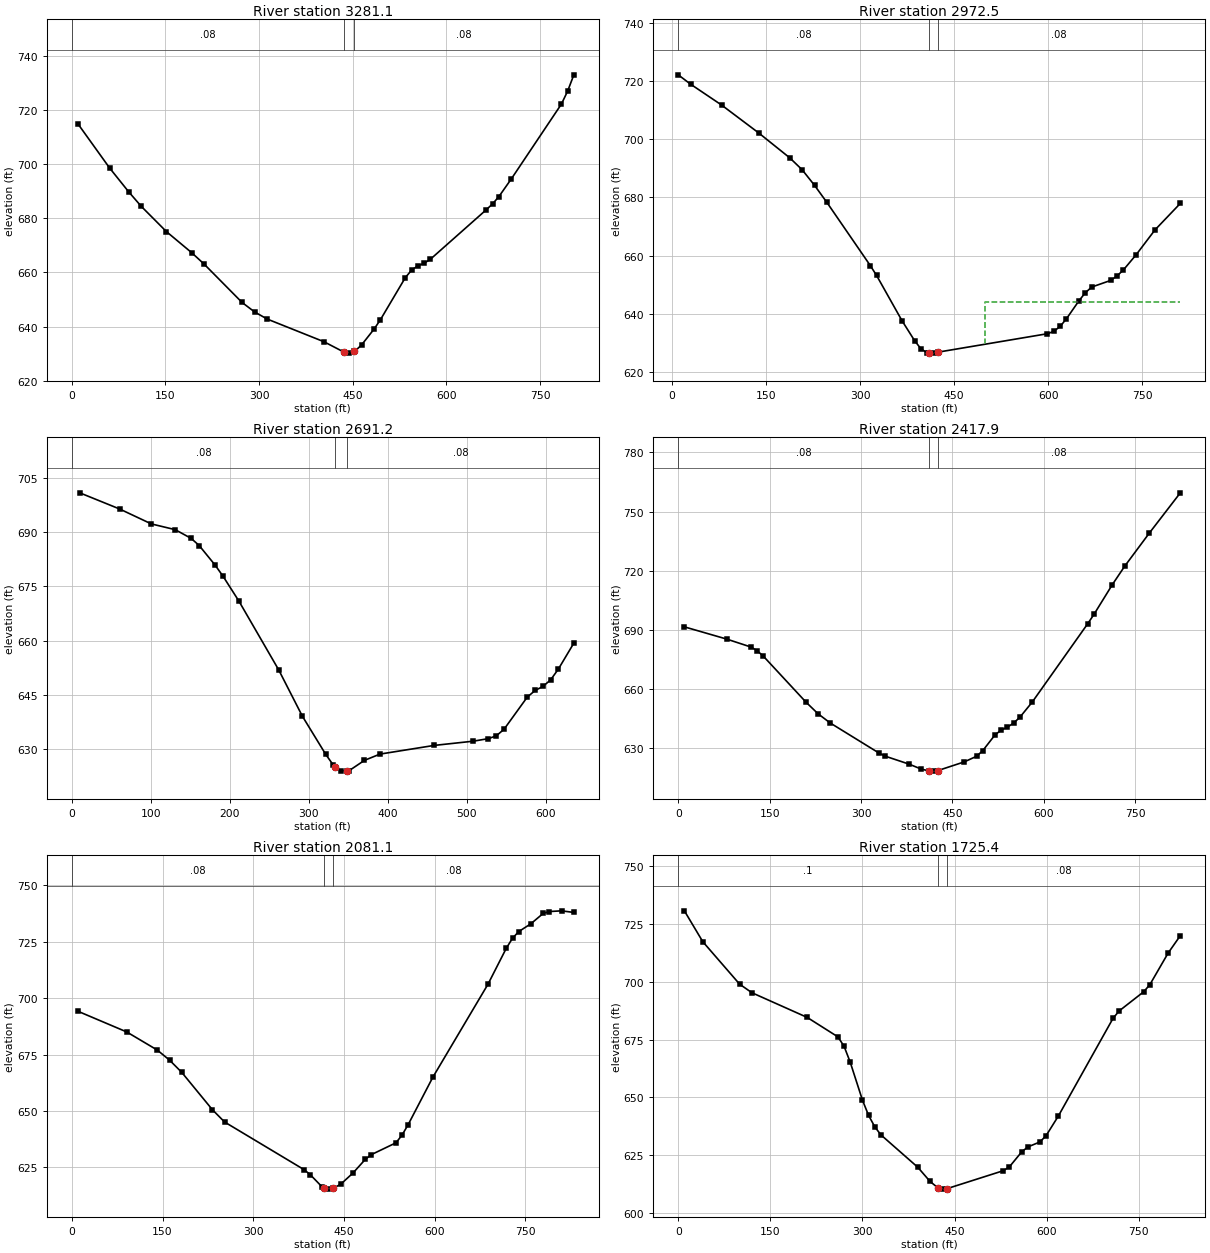
Type RM Length L Ch R = 1 ,3281.1  ,311,308.6,306.8
XS GIS Cut Line= 3
     1563331.651      455800.228     1563302.746      456243.608
     1563297.847      456603.429
#Sta/Elev= 30
    10.1  714.75    60.6  698.53    90.9  689.81   111.1  684.42   151.5  675.07
   191.9   667.3   212.1  663.03   272.7  648.91   292.8   645.4     313  642.77
   403.9   634.4   436.8  630.47   444.3  630.19   451.8  630.85   454.3  631.07
   464.3  633.25   484.3  639.09   494.3  642.49   534.3  658.07   544.3  660.83
   554.3   662.4   564.3  663.37   574.3  664.82   664.2  683.17   674.2  685.33
   684.2     688   704.2  694.55   784.2  722.09   794.2  726.88   804.2  732.92
#Mann= 3 , 0 , 0
       0     .08       0   436.8    .045       0   451.8     .08       0
Bank Sta=436.8,451.8
XS Rating Curve= 0 ,0
Exp/Cntr=0.3,0.1

Type RM Length L Ch R = 1 ,2972.5  ,305.6,281.3,257.1
XS GIS Cut Line= 3
     1562848.052      455846.871     1563007.376      456120.034
     1563057.233        456612.1
#Sta/Elev= 30
     9.9  722.05    29.6  718.84    79.1  711.68   138.4  702.09   187.8  693.57
   207.5   689.5   227.3  684.15   247.1  678.26   316.2  656.64   326.3  653.22
   366.7  637.76   386.9  630.87     397  628.08   407.1  626.65   409.7  626.63
   417.2  626.58   424.7  626.93   598.9  633.24   608.9  634.04     619  635.72
   629.1  638.35   649.3  644.59   659.4  647.33   669.5  649.25   699.8  651.53
   709.9  653.07     720  655.12   740.2  660.29   770.4  668.85   810.8  677.94
#Mann= 3 , 0 , 0
     9.9     .08       0   409.7    .045       0   424.7     .08       0
#XS Ineff= 2 , 0
                          498.56           644.2
Permanent Ineff=
       F       F
Bank Sta=409.7,424.7
XS Rating Curve= 0 ,0
Exp/Cntr=0.3,0.1

Type RM Length L Ch R = 1 ,2691.2  ,272.6,273.3,274.2
XS GIS Cut Line= 4
     1562602.018      456120.034      1562768.93      456347.642
     1562931.507      456417.008     1563029.053      456564.411
#Sta/Elev= 30
    10.1  700.95    60.5  696.48   100.8  692.33     131  690.74   151.2  688.32
   161.3  686.35   181.4  680.95   191.5  677.85   211.7  670.92   262.1  651.85
   292.1     639   321.5  628.49   331.3  625.45   333.7  625.05   341.2  623.81
   348.7  623.88     351  623.91   370.6  626.79   390.3  628.53     459  630.94
   508.1   632.1   527.7  632.82   537.6   633.6   547.4  635.41   576.8  644.32
   586.7  646.16   596.5  647.27   606.3  649.08   616.1  652.06   635.8   659.3
#Mann= 3 , 0 , 0
       0     .08       0   333.7    .045       0   348.7     .08       0
Bank Sta=333.7,348.7
XS Rating Curve= 0 ,0
Exp/Cntr=0.3,0.1

Type RM Length L Ch R = 1 ,2417.9  ,328.2,336.8,343.2
XS GIS Cut Line= 3
     1562376.578      456456.026     1562756.164      456633.401
     1563120.696      456810.307
#Sta/Elev= 30
      10   691.6    79.8  685.37   119.7  681.33   129.7  679.44   139.7  676.74
   209.5   653.5   229.4  647.57   249.4  642.89   329.2  627.71   339.2  626.11
   379.1     622     399  619.49   411.5  618.59     419  618.47   426.5  618.78
   469.6  623.16   489.9  626.02     500   628.9   520.3  636.94   530.4  639.29
   540.5  640.79   550.7  642.87   560.8  645.77   581.1  653.46   672.2  693.18
   682.4  697.88   712.7  713.04     733  722.37   773.5  739.19   824.2  759.52
#Mann= 3 , 0 , 0
       0     .08       0   411.5    .045       0   426.5     .08       0
Bank Sta=411.5,426.5
XS Rating Curve= 0 ,0
Exp/Cntr=0.3,0.1

Type RM Length L Ch R = 1 ,2081.1  ,339.4,355.6,373.6
XS GIS Cut Line= 3
     1562220.504      456536.231     1562510.768      456845.743
     1562811.258      457118.238
#Sta/Elev= 30
    10.1   694.2    90.9  685.01   141.4  676.97   161.6  672.53   181.9  667.06
   232.4  650.54   252.6  645.07   383.9  623.95     394  621.77   414.2  616.17
   416.8  615.94   424.3  615.29   431.8  615.63   444.6  617.46   464.9  622.44
   485.2  628.48   495.3   630.6   535.9  635.83     546  639.26   556.2  643.95
   596.7  664.83     688  706.16   718.4  722.17   728.6  726.57   738.7  729.49
     759  733.01   779.3  737.58   789.4  738.42   809.7  738.74     830  738.02
#Mann= 3 , 0 , 0
       0     .08       0   416.8    .045       0   431.8     .08       0
Bank Sta=416.8,431.8
XS Rating Curve= 0 ,0
Exp/Cntr=0.3,0.1

Type RM Length L Ch R = 1 ,1725.4  ,468,460.2,454.3
XS GIS Cut Line= 3
     1562159.809      456466.865     1562168.138      456876.954
     1562187.989      457284.084
#Sta/Elev= 30
      10  730.79      40  717.42     100  699.03   120.1  695.31   210.1  684.63
   260.1  676.21   270.1  672.14   280.1  665.27   300.1  648.78   310.1  642.19
   320.1  637.28   330.1  633.78   390.2  619.75   410.2   613.6   422.6  610.92
   430.1  610.28   437.6  610.47   529.5  618.26   539.4  619.93   559.3  626.36
   569.2  628.52   589.1  630.71   599.1   633.4     619  641.86   708.4  684.32
   718.4  687.49   758.1  695.73   768.1  698.78   797.9  712.48   817.8  720.04
#Mann= 3 , 0 , 0
       0      .1       0   422.6    .045       0   437.6     .08       0
Bank Sta=422.6,437.6
XS Rating Curve= 0 ,0
Exp/Cntr=0.3,0.1

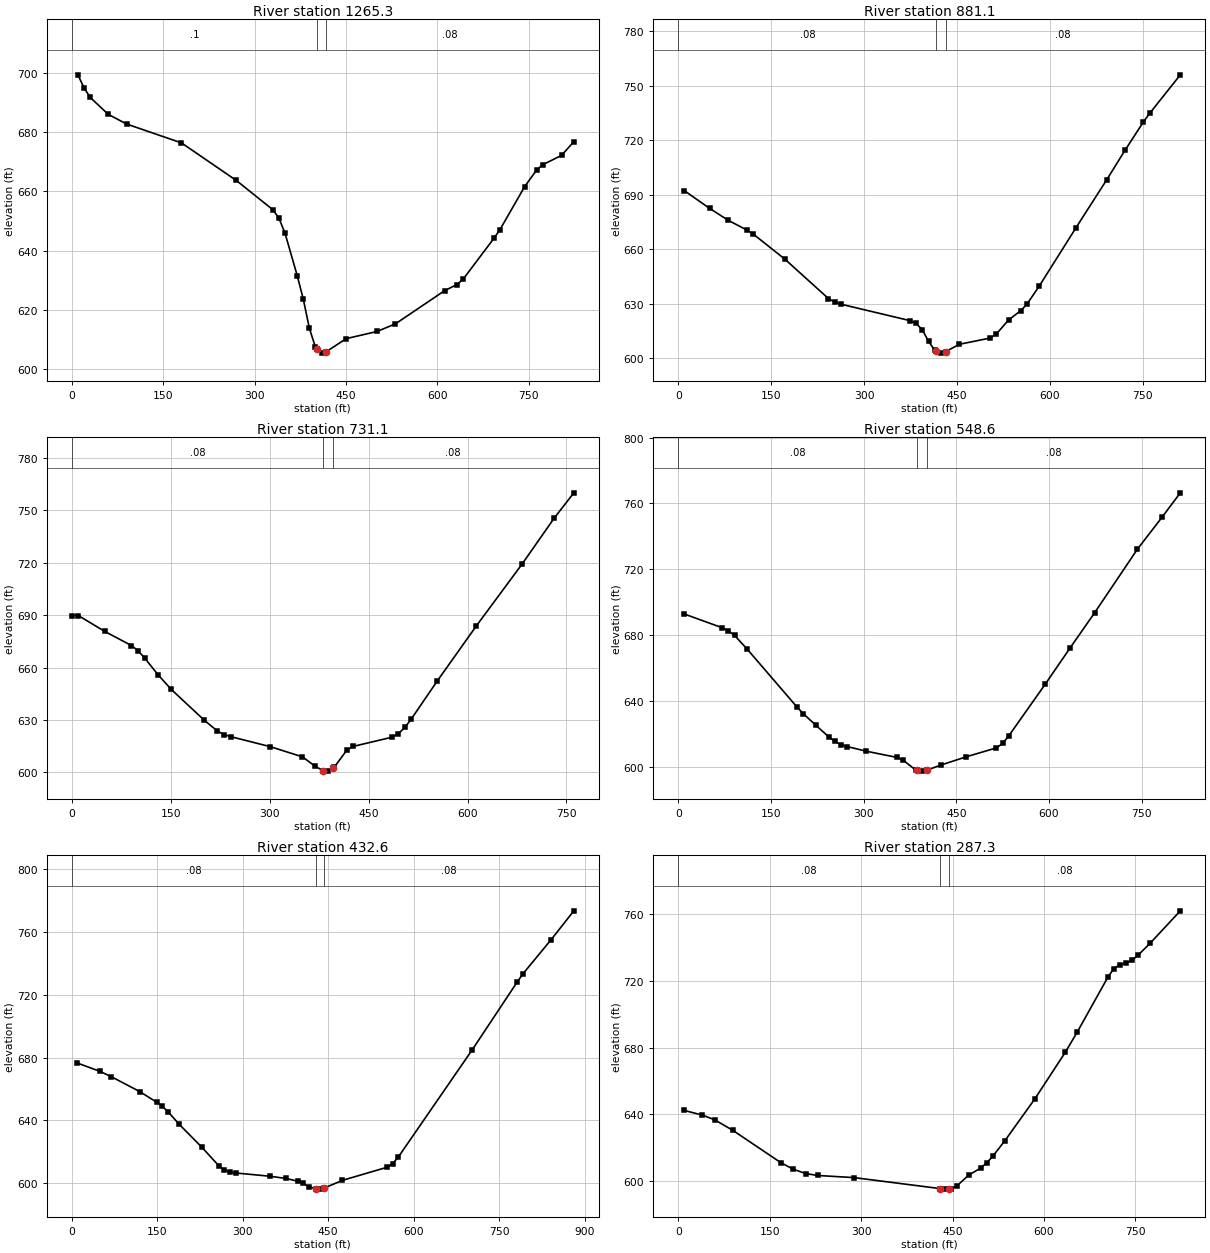
Type RM Length L Ch R = 1 ,1265.3  ,383,384.2,382.4
XS GIS Cut Line= 3
     1561560.178      456557.641     1561715.432      456937.254
     1561837.457      457332.963
#Sta/Elev= 30
      10  699.26      20  694.95      30  691.69      60  685.93      90  682.68
   180.1  676.32   270.1  663.66   330.1   653.8   340.1  650.95   350.1  645.85
   370.1  631.59   380.1  623.62   390.1  613.81   400.1  607.39   402.6  606.91
   410.1  605.47   417.6  605.94   450.5  610.35     501  612.76   531.3  615.33
   612.1  626.52   632.3  628.59   642.4  630.37   692.9  644.13     703  647.12
   743.4  661.57   763.6  667.33   773.7  669.02     804  672.12   824.2  676.75
#Mann= 3 , 0 , 0
       0      .1       0   402.6    .045       0   417.6     .08       0
Bank Sta=402.6,417.6
XS Rating Curve= 0 ,0
Exp/Cntr=0.3,0.1

Type RM Length L Ch R = 1 ,881.1   ,139,150,162.1
XS GIS Cut Line= 3
     1561227.723       456691.92     1561367.577      457092.565
     1561511.669      457450.997
#Sta/Elev= 30
    10.1  692.18    50.5  682.49    80.8  675.88   111.1  670.49   121.2  668.28
   171.8  654.59   242.5   632.8   252.6  630.78   262.7  629.67   373.8  620.65
   383.9  619.15     394  615.64   404.1  609.24   414.2  604.26   416.9  603.85
   424.4  602.71   431.9  603.59   454.1  607.59   503.6  611.01   513.5  613.17
   533.3  620.94   553.1  626.14     563  629.66   582.8  639.59   642.3  671.84
   691.8  698.18   721.5  714.53   751.2  730.15   761.1  734.76   810.7  756.05
#Mann= 3 , 0 , 0
       0     .08       0   416.9    .045       0   431.9     .08       0
Bank Sta=416.9,431.9
XS Rating Curve= 0 ,0
Exp/Cntr=0.3,0.1

Type RM Length L Ch R = 1 ,731.1   ,186.8,182.5,178.1
XS GIS Cut Line= 4
     1561187.256      456736.934     1561233.931      457044.643
     1561213.187      457177.753     1561335.925      457468.175
#Sta/Elev= 30
       0   689.8      10   689.8    50.2  680.67    90.4  672.64   100.4  669.71
   110.4  665.53   130.5  656.05   150.6  647.59   200.8  629.91   220.9  623.66
   230.9  621.66     241  620.47   301.2  614.71   349.7  608.91     369  603.51
   380.7  601.03   388.2  600.73   395.7  602.42   397.8  602.89   417.1   612.8
   426.7  614.89   485.4  620.14   495.2  622.17   505.1  625.78   514.9  630.65
   554.3  652.45   613.4  683.88   682.4  719.12   731.7  745.72   761.2  760.06
#Mann= 3 , 0 , 0
       0     .08       0   380.7    .045       0   395.7     .08       0
Bank Sta=380.7,395.7
XS Rating Curve= 0 ,0
Exp/Cntr=0.3,0.1

Type RM Length L Ch R = 1 ,548.6   ,133.2,116,98.8
XS GIS Cut Line= 3
     1561036.403      456710.188     1561044.532      457195.209
     1561152.916      457504.105
#Sta/Elev= 30
    10.1   692.9      71  684.62    81.1  682.79    91.2  679.93   111.5  671.66
   192.6  636.31   202.7  632.36     223  625.31   243.3  618.52   253.4  615.62
   263.5  613.65   273.7   612.5   303.9  609.73   354.2   605.9   364.3  604.15
   384.5  598.21     387  598.06   394.5  597.61     402  598.15   424.7  601.24
     465  606.18   514.9  611.71   524.9  614.39   534.8  618.95   594.3  650.58
     634  672.29   673.7  693.62   743.1  732.29   782.8   751.6   812.5  766.47
#Mann= 3 , 0 , 0
       0     .08       0     387    .045       0     402     .08       0
Bank Sta=387,402
XS Rating Curve= 0 ,0
Exp/Cntr=0.3,0.1

Type RM Length L Ch R = 1 ,432.6   ,137.5,145.2,153
XS GIS Cut Line= 4
     1560834.331      456723.019     1560887.374      457075.986
     1561003.888      457195.209     1561126.525      457530.851
#Sta/Elev= 30
     9.9  676.51    49.6   671.2    69.4  667.83     119  658.39   148.7  651.67
   158.6  649.02   168.6  645.63   188.4  637.55     228  623.01   257.8   611.2
   267.7  608.36   277.6  607.04   287.5  606.52     347  604.47   376.5     603
   396.2   601.3     406  599.86   415.8   597.8   427.9  596.41   435.4  596.23
   442.9   596.9   474.6  601.78   553.4  610.17   563.3  612.52   573.3  616.82
   702.3  684.74   781.7  728.19   791.6  733.29   841.3  755.16     881  773.45
#Mann= 3 , 0 , 0
       0     .08       0   427.9    .045       0   442.9     .08       0
Bank Sta=427.9,442.9
XS Rating Curve= 0 ,0
Exp/Cntr=0.3,0.1

Type RM Length L Ch R = 1 ,287.3   ,226.8,228.5,230.2
XS GIS Cut Line= 4
      1560666.27      456820.199     1560781.157      457106.334
     1560867.865      457294.923     1560991.424      457576.723
#Sta/Elev= 30
     9.9  642.36    39.8  639.52    59.7  636.75    89.5  630.42   169.1  610.84
     189  607.07   208.9  604.52   228.8  603.34   288.4  602.07   429.3   595.5
   436.8  595.16   444.3  595.22   446.7  595.23   456.6  596.92   476.4  603.56
   496.1  607.78     506  610.93   515.9  614.85   535.8  624.18   585.4  649.51
     635  677.27   654.9   689.6   704.5  722.09   714.4  727.37   724.3  729.77
   734.3   730.6   744.2  732.42   754.1  735.42     774  742.58   823.6  762.07
#Mann= 3 , 0 , 0
       0     .08       0   429.3    .045       0   444.3     .08       0
Bank Sta=429.3,444.3
XS Rating Curve= 0 ,0
Exp/Cntr=0.3,0.1

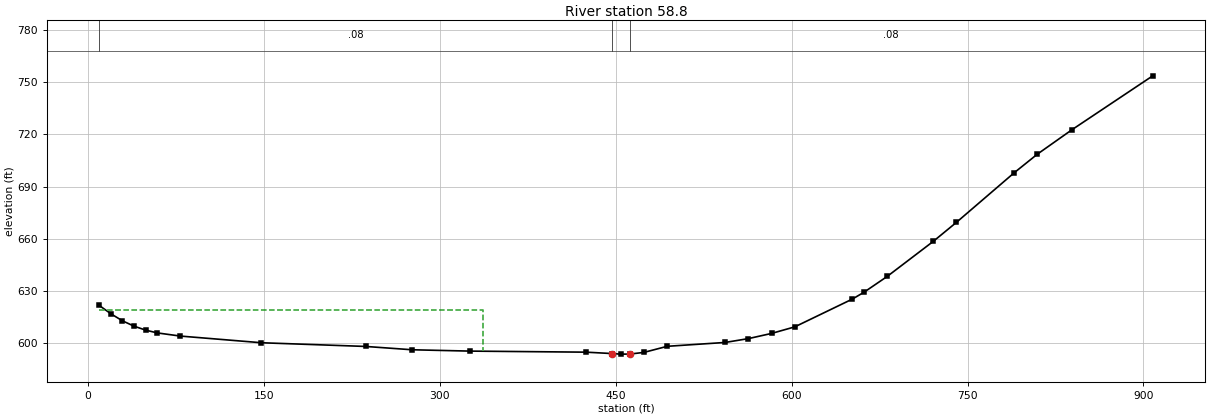
Type RM Length L Ch R = 1 ,58.8    ,62,58.8,55.7
XS GIS Cut Line= 4
     1560648.928      456872.223     1560577.395      457180.035
     1560677.108      457448.829     1560922.057      457630.915
#Sta/Elev= 30
     9.9  621.52    19.8  616.73    29.6   612.7    39.5  609.62    49.4  607.34
    59.3  605.74      79  603.92   148.1  600.08     237  597.95   276.5  596.04
   325.9  595.27   424.8  594.66   446.9  593.86   454.4  593.53   461.9  593.55
   474.2  594.53     494  598.03   543.4  600.25   563.2  602.46   582.9  605.44
   602.7  609.21   651.9  625.24   661.8  629.17   681.5  638.23   720.9  658.47
   740.5  669.34   789.8  697.91   809.5   708.6     839  722.66   907.9   753.7
#Mann= 3 , 0 , 0
     9.9     .08       0   446.9    .045       0   461.9     .08       0
#XS Ineff= 2 , 0
          336.84  618.87
Permanent Ineff=
       F       F
Bank Sta=446.9,461.9
XS Rating Curve= 0 ,0
Exp/Cntr=0.3,0.1
Stream Node=MFWILSONCR      ,Main            , 0 , 0 ,Upstream end
Stream Node=MFWILSONCR      ,Main            , 0 , 1 ,Downstream end

Chan Stop Cuts=-1
Use User Specified Reach Order=0